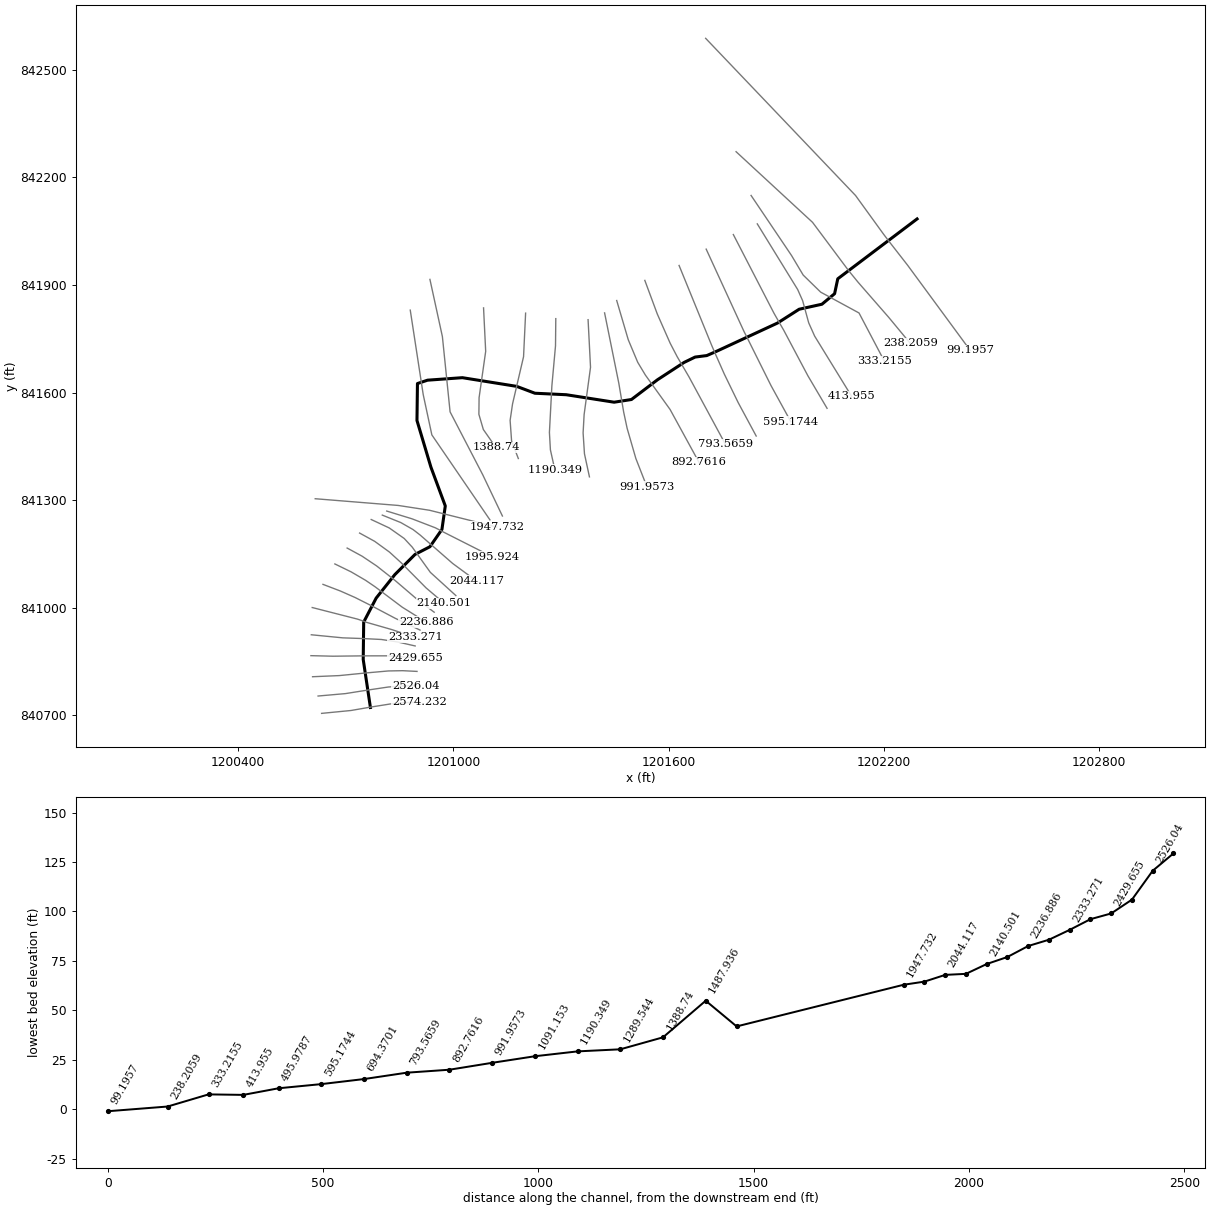
--- 233_ras.prj (project) ---

Proj Title=233
Current Plan=p01
Default Exp/Contr=0.3,0.1
English Units
Geom File=g01
Flow File=f01
Plan File=p01
Y Axis Title=Elevation
X Axis Title(PF)=Main Channel Distance
X Axis Title(XS)=Station
BEGIN DESCRIPTION:
RFD model 233 exported to HEC-RAS
END DESCRIPTION:

--- 233_ras.p01 (plan) ---

Plan Title=Plan 01
Program Version=4.10
Short Identifier=Plan 01
Geom File=g01
Flow File=f01
Subcritical Flow
Calc Critical at every XS
Secant Critical Depth

--- 233_ras.f01 (steady flow) ---

Flow Title=Flow 01
Program Version=5.01
Number of Profiles= 5
Profile Names=10yr,25yr,50yr,100yr,500yr
River Rch & RM=233,30,2574.232
  102.43  181.42  257.06  346.98  608.29
River Rch & RM=233,30,2477.848
  109.93  195.01  276.72  374.12  658.68
River Rch & RM=233,30,2333.271
  113.05  200.67  284.92  385.45  679.78
River Rch & RM=233,30,2236.886
   114.3  202.93   288.2  389.98  688.24
River Rch & RM=233,30,2140.501
  116.79  207.46  294.76  399.06  705.18
River Rch & RM=233,30,2092.309
  123.02  218.77  311.17  421.77  747.67
River Rch & RM=233,30,1559.786
  154.03  275.27  393.38  535.93  963.11
River Rch & RM=233,30, 1388.74
  158.35  283.17  404.91  551.98  993.62
River Rch & RM=233,30,1289.544
  162.67  291.07  416.45  568.05 1024.22
River Rch & RM=233,30,1190.349
  166.99  298.97  427.98  584.14  1054.9
River Rch & RM=233,30,1091.153
  175.01  313.64  449.42  614.05 1112.08
River Rch & RM=233,30,991.9573
  201.43  362.12  520.42  713.32 1302.95
River Rch & RM=233,30,892.7616
  205.72     370  531.99  729.53 1334.26
River Rch & RM=233,30,694.3701
  211.24  380.14  546.87  750.38 1374.61
River Rch & RM=233,30,595.1744
  217.36   391.4  563.41  773.58 1419.56
River Rch & RM=233,30,495.9787
  224.09  403.79  581.61  799.12 1469.15
River Rch & RM=233,30,333.2155
  225.92  407.17  586.57  806.09  1482.7
River Rch & RM=233,30, 99.1957
  230.81  416.17  599.82  824.69 1518.88
Boundary for River Rch & Prof#=233,30,1
Up Type= 0
Dn Type= 2
Boundary for River Rch & Prof#=233,30,2
Up Type= 0
Dn Type= 2
Boundary for River Rch & Prof#=233,30,2
Up Type= 0
Dn Type= 2
Boundary for River Rch & Prof#=233,30,2
Up Type= 0
Dn Type= 2
Boundary for River Rch & Prof#=233,30,2
Up Type= 0
Dn Type= 2

--- 233_ras.g01 (geometry) ---

Geom Title=233
Program Version=4.10

River Reach=233,30
Reach XY= 30
1200768.87793222840721.933662578 1200748.8080076840855.733159915
1200750.14600256840960.096767828 1200784.9338719841026.996516511
1200837.11567584841092.558270186 1200893.3114647841148.754059061
1200934.78930888841170.1619786471200968.23918325841218.329797685
1200977.60514805 841283.891551391200937.46529889841392.269144207
1200898.66344461841522.0546566251200900.00143957841625.080269575
1200928.09933403841634.4462344051201025.28336418841641.428566918
 1201176.5917531841617.2326859531201227.42507091841598.066023514
1201314.92504513841593.8993555011201448.25833869841573.066024467
1201496.59165806841580.5660208461201569.09163839841635.566002533
1201643.25828466 841683.899319411201674.09160936841698.899314091
1201706.59159991841703.0659785721201733.25825912841714.732641041
 1201904.0915446841793.8992793561201964.09152806841832.232599601
1202027.61105844 841846.203642131202062.91980872841875.527493328
1202071.76098207841917.0758879181202292.85420683842084.012545437

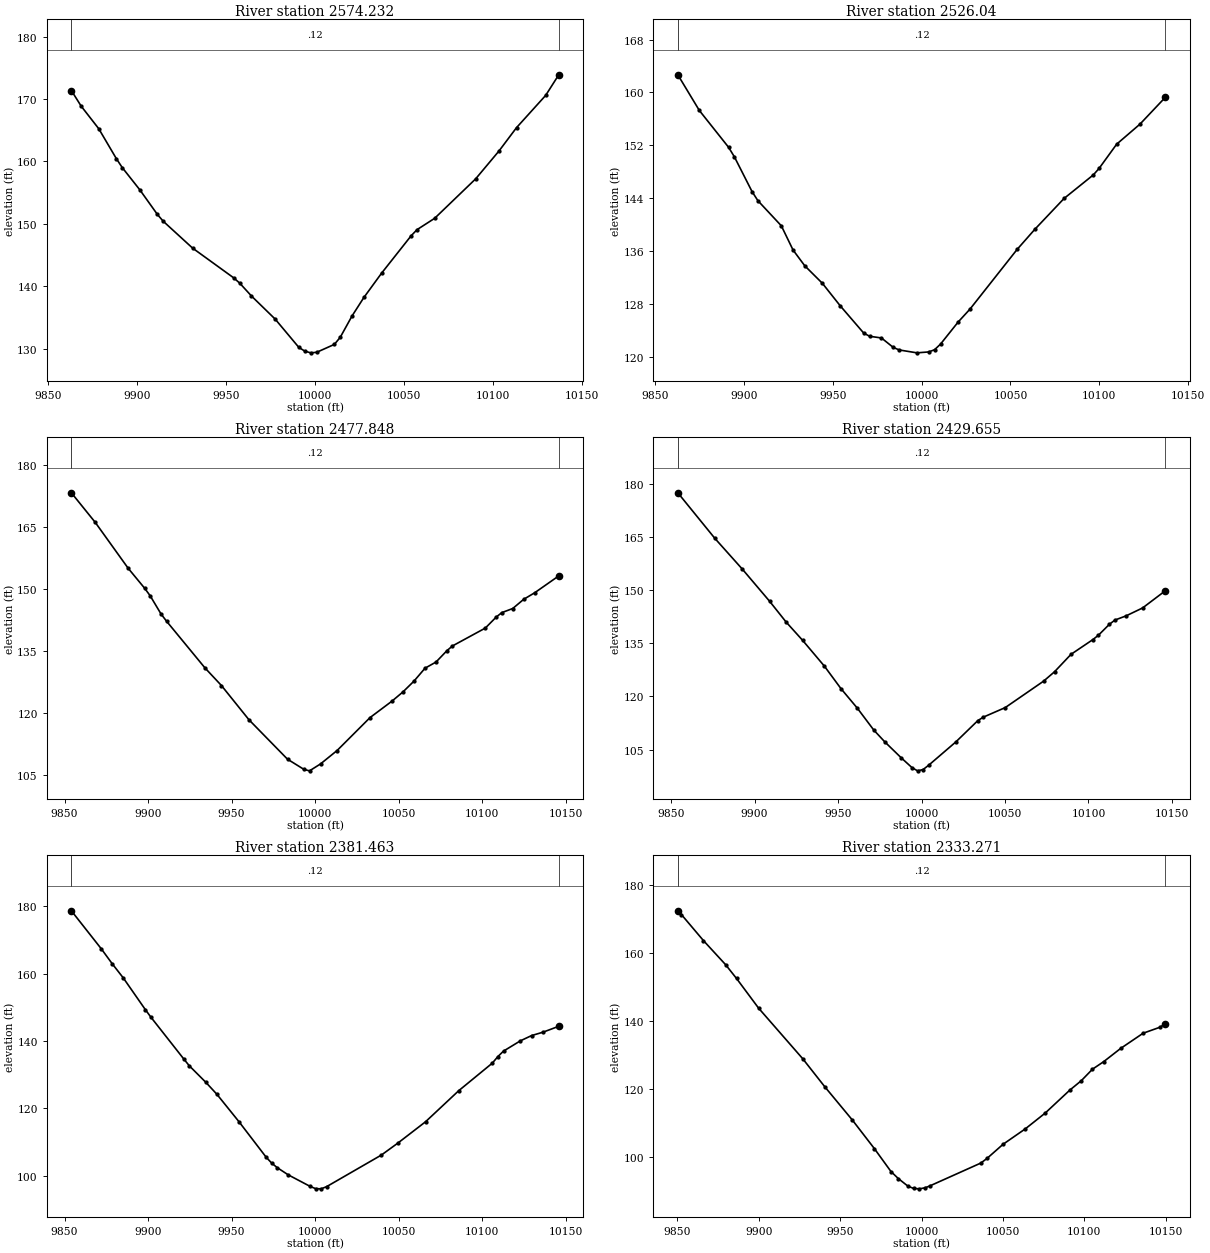
Type RM Length L Ch R = 1 ,2574.232,48.192400,48.192400,48.192400
XS GIS Cut Line= 6
1200632.79815389840705.569250815 1200714.5467542840713.576087404
1200769.65659078840723.1142094231200828.23576339840732.429407851
1200864.32659166840735.4850430471200904.84833915840736.466492093
#Sta/Elev= 30
 9862.93171.36019868.464168.85269878.353165.23859888.243160.4502 9891.54159.0263
9901.429155.46549911.319151.52239914.615150.42589931.098146.13499954.263141.3627
9957.592140.5312 9964.25138.45679977.566134.76429990.882 130.2369994.211129.6408
 9997.54129.364910000.88129.448910010.85130.714910014.17131.855710020.81135.2741
10027.46138.226810037.42142.119910054.03148.102510057.36149.085710067.26150.8993
10090.31157.212710103.46 161.682 10113.3165.411510129.71170.580710137.07173.8773
#Mann= 3 , 0 , 0
 9862.93    0.12       0 9862.93    0.12       010137.07    0.12       0
#XS Ineff= 2 , 0
       0                               0
Bank Sta=9862.93,10137.07
Exp/Cntr=0.3,0.1

Type RM Length L Ch R = 1 , 2526.04,48.192300,48.192300,48.192300
XS GIS Cut Line= 6
1200622.95887523840753.9448549381200699.44303269840760.722708664
1200759.97262278840770.323553239 1200818.6448206840779.060067593
1200854.75090906840781.9237975451200895.27922803840782.465708121
#Sta/Elev= 30
9862.928162.67019875.041157.26539891.509151.68529894.803150.22059904.684144.9864
9907.978143.61039921.152139.8104 9927.74136.14619934.327133.75999944.246131.1047
9954.209127.72199967.493123.57019970.814  123.099977.456122.83469984.098121.4054
9987.419121.02139997.383120.582910004.04120.718610007.35121.058810010.67 121.901
10020.62125.255410027.26127.203210053.79136.245310063.72139.277110080.17143.9499
10096.63147.516210099.91148.513310109.75152.165910122.88 155.20410137.07159.2432
#Mann= 3 , 0 , 0
9862.928    0.12       09862.928    0.12       010137.07    0.12       0
#XS Ineff= 2 , 0
       0                               0
Bank Sta=9862.928,10137.07
Exp/Cntr=0.3,0.1

Type RM Length L Ch R = 1 ,2477.848,48.192300,48.192300,48.192300
XS GIS Cut Line= 6
1200607.58955077840807.7238312631200682.24723143840810.928793486
1200754.13792893840818.058177648 1200819.1360487840823.855456035
1200858.96962822840824.5780560871200898.78190518840822.556884768
#Sta/Elev= 30
 9854.03173.26649868.355166.09839888.058155.0028 9897.91150.17499901.193148.3735
9907.761143.93559911.045142.19619934.053130.89659943.943126.62369960.427118.3399
9983.505108.80829993.395106.33069996.692105.994210003.29107.675610013.17110.9029
10032.93118.881710046.11122.871910052.69125.107210059.28127.716410065.87130.8301
10072.43132.3147   10079135.077410082.28136.206510101.97140.533610108.53143.2112
10111.82144.267510118.39145.267910124.96147.493910131.53149.074810145.96153.1594
#Mann= 3 , 0 , 0
 9854.03    0.12       0 9854.03    0.12       010145.96    0.12       0
#XS Ineff= 2 , 0
       0                               0
Bank Sta=9854.03,10145.96
Exp/Cntr=0.3,0.1

Type RM Length L Ch R = 1 ,2429.655,48.192400,48.192400,48.192400
XS GIS Cut Line= 6
1200602.98355046840866.4697234931200664.36163442840864.941543672
1200747.93827588840865.9004956281200815.20232798840865.985862162
1200854.97805014 840863.724600911200894.53879869840858.810186814
#Sta/Elev= 30
9854.021177.46149876.226164.58869892.636155.93269909.045146.82569918.889140.9907
9928.733135.84949941.857128.5216  9951.7122.23039961.543116.69079971.386110.5224
9977.948107.20749987.791102.70429994.35499.884059997.63599.0086210000.9299.36958
 10004.2100.5601 10020.6107.190910033.72113.1821   10037114.157310050.13116.8519
10073.11124.314110079.68126.973410089.54131.882410102.68136.055610105.97 137.281
10112.58140.384110115.88141.5594 10122.5142.729110132.41144.966810145.97149.7972
#Mann= 3 , 0 , 0
9854.021    0.12       09854.021    0.12       010145.97    0.12       0
#XS Ineff= 2 , 0
       0                               0
Bank Sta=9854.021,10145.97
Exp/Cntr=0.3,0.1

Type RM Length L Ch R = 1 ,2381.463,48.192300,48.192300,48.192300
XS GIS Cut Line= 6
1200604.04407877840924.7209756951200691.68271835840916.133422969
1200750.55591123840914.0632339721200799.50960924840911.571712536
1200845.47972816840904.5202110911200893.65761466840893.507311459
#Sta/Elev= 30
9854.032178.68169871.974167.38159878.567162.91149885.161158.72299898.347 149.329
9901.643147.10589921.423134.63089924.719132.62189934.609127.72719941.202124.1846
9954.337116.09839970.752105.46899974.035103.73569977.318102.40349983.884100.2712
9997.01696.83933 10000.396.1669510003.5896.1059210006.8796.7464710039.72106.1435
10049.57109.688410066.16116.025710086.08 125.27310106.13133.426210109.49135.3879
10112.86137.011610122.95140.057210129.69141.627810136.42 142.61410145.95144.3778
#Mann= 3 , 0 , 0
9854.032    0.12       09854.032    0.12       010145.95    0.12       0
#XS Ineff= 2 , 0
       0                               0
Bank Sta=9854.032,10145.95
Exp/Cntr=0.3,0.1

Type RM Length L Ch R = 1 ,2333.271,48.192300,48.192300,48.192300
XS GIS Cut Line= 6
1200606.64959573841000.6466241321200732.97829413 840968.32233913
1200750.25892514840962.4814655251200757.15327335840959.630400799
1200827.80346346840939.3818329941200893.98238173840917.547874194
#Sta/Elev= 30
 9850.36172.39039852.557171.28949866.103163.6303 9879.65 156.5879886.423152.5008
9899.969143.78549927.061128.93079940.607120.6953 9957.54110.91789971.086  102.51
9981.25795.790989985.71193.748939991.64691.504639995.10990.834389998.572 90.7119
10002.1891.0131910004.9391.5332510036.4298.2869610040.2299.6480110050.07103.8013
10063.72108.326210075.94112.965110091.16119.757310098.07122.462710104.98125.8603
10111.89128.084610122.26131.950910136.07136.420910146.44138.187610149.65139.1955
#Mann= 3 , 0 , 0
 9850.36    0.12       0 9850.36    0.12       010149.65    0.12       0
#XS Ineff= 2 , 0
       0                               0
Bank Sta=9850.36,10149.65
Exp/Cntr=0.3,0.1

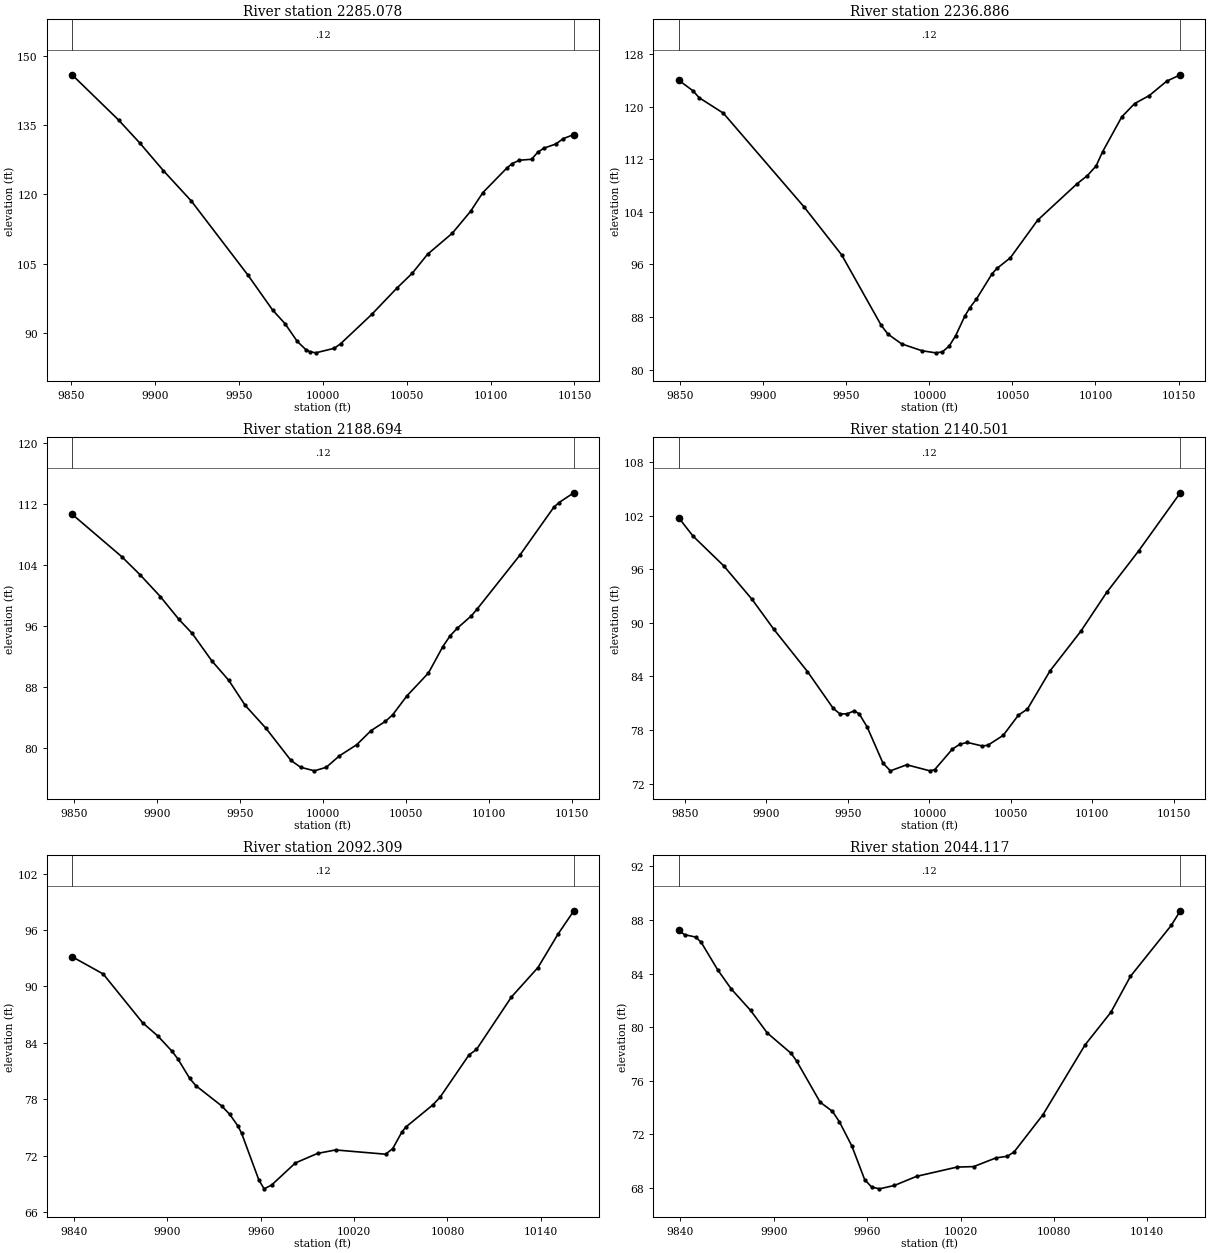
Type RM Length L Ch R = 1 ,2285.078,48.192400,48.192400,48.192400
XS GIS Cut Line= 6
1200636.62475764 841065.217511741200684.83795631841046.819682429
 1200726.1477934841028.5908179941200772.49259187841005.238516911
1200837.73942854840970.7685481241200907.17528722840937.799079002
#Sta/Elev= 30
9850.347145.84959878.111136.06279890.773131.08419904.881125.09479921.531118.5331
9955.281 102.5139969.97694.974679977.32392.054699984.67188.19529 9989.7886.41675
9992.01985.998279995.69285.7207110006.7886.70932 10010.587.6781610029.05 94.0137
10043.8999.6445410053.34102.969110062.45107.0604 10077.2111.600710088.09116.3475
10095.36120.365410109.88125.756710112.79126.620510117.15127.370510124.41127.5771
10128.04129.061610131.67129.963610138.94130.885310143.38 132.05710149.66132.9093
#Mann= 3 , 0 , 0
9850.347    0.12       09850.347    0.12       010149.66    0.12       0
#XS Ineff= 2 , 0
       0                               0
Bank Sta=9850.347,10149.66
Exp/Cntr=0.3,0.1

Type RM Length L Ch R = 1 ,2236.886,48.192300,48.192300,48.192300
XS GIS Cut Line= 6
1200669.80039961841122.1308394591200715.11107163 841100.05639098
1200755.57126625841076.4275399331200782.05663586841058.373894018
1200857.65887575841001.5603270651200924.10893768840960.118119907
#Sta/Elev= 30
9848.895124.05819857.655122.41329861.305121.37479875.903119.01689924.333104.8006
9947.17397.437249970.99786.711399974.96785.399849983.22983.907099995.49782.86125
10003.7682.5418610007.8682.6913510011.9583.59539 10015.885.1597610021.2988.12674
10024.2389.3769210028.3390.7385410037.7494.5871810040.6195.3790510048.7297.00617
10065.17102.737210088.79108.252710095.18109.533410100.39110.999110104.25113.1339
10115.85118.466410123.59120.486610132.38121.698810142.92123.895710151.09124.8634
#Mann= 3 , 0 , 0
9848.895    0.12       09848.895    0.12       010151.09    0.12       0
#XS Ineff= 2 , 0
       0                               0
Bank Sta=9848.895,10151.09
Exp/Cntr=0.3,0.1

Type RM Length L Ch R = 1 ,2188.694,48.192400,48.192400,48.192400
XS GIS Cut Line= 6
 1200703.9638281841166.4835114271200745.68854617841143.764076653
1200786.34990546841116.5180372561200836.99554204841076.639599901
1200902.88309425841020.2349663271200946.63410023840987.635415704
#Sta/Elev= 30
9848.902110.6828 9878.74105.12429889.947 102.7139902.05899.873769913.27396.86822
9921.17295.05606 9933.0291.447999943.31588.864549953.17685.589329965.67882.58552
9980.75578.358399986.51677.472869994.85276.99748   1000277.4656210009.8278.94933
10020.3580.4287510028.9982.2814410037.63 83.496610041.95 84.342710050.5986.84178
10063.5489.8415310072.1893.29736 10076.5 94.698410080.8295.6991310089.4697.36216
10093.0598.2849310118.47105.271110138.93111.562110142.16 112.21310151.11113.4934
#Mann= 3 , 0 , 0
9848.902    0.12       09848.902    0.12       010151.11    0.12       0
#XS Ineff= 2 , 0
       0                               0
Bank Sta=9848.902,10151.11
Exp/Cntr=0.3,0.1

Type RM Length L Ch R = 1 ,2140.501,48.192300,48.192300,48.192300
XS GIS Cut Line= 6
1200738.72166314841208.2814037021200780.85717015841185.133138406
1200822.09535463841155.1530866291200855.40851231841124.738076462
1200924.11362619841055.2993290431200974.55795326841012.493141989
#Sta/Elev= 30
9846.011101.7713 9854.9799.684819873.68696.383459891.13992.617329904.43189.28513
 9925.1584.540089940.93780.426789945.07179.799799949.42879.808579953.871 80.1385
9956.89279.808849961.75878.34778 9971.4974.295429976.08373.430169986.08874.10808
10000.2573.4327910003.2673.5651510014.0875.8585110018.6976.40821 10023.376.60819
10032.52 76.205710035.9576.30233 10045.377.3988610054.6479.6621310060.1880.34334
10074.0184.60904 10092.989.0378210108.8993.41493 10128.4 98.030510154.02104.5436
#Mann= 3 , 0 , 0
9846.011    0.12       09846.011    0.12       010154.02    0.12       0
#XS Ineff= 2 , 0
       0                               0
Bank Sta=9846.011,10154.02
Exp/Cntr=0.3,0.1

Type RM Length L Ch R = 1 ,2092.309,48.192300,48.192300,48.192300
XS GIS Cut Line= 6
1200771.09180155841246.018327786 1200821.4616911841222.448185431
1200863.05113647841193.1561549461200885.47234432841168.989566073
1200936.02213638841098.6518052521201007.10078724841033.958803414
#Sta/Elev= 30
9838.78793.165089858.80691.326899884.16286.132089893.94284.722899902.81583.14517
9906.68682.313369914.42980.20958  9918.379.448899934.84777.30208 9940.1376.38602
9945.40375.150849947.74574.380339958.82969.410879962.21668.46728 9967.0468.87281
9982.28171.218059996.54172.2372810008.1572.6038310040.2972.1521910044.85 72.7463
10050.7474.5041310053.2975.0437510070.67 77.400310075.3278.21881 10093.982.71886
10098.6983.2929210121.1788.8798710138.2292.0158110151.0195.5489710161.2898.05164
#Mann= 3 , 0 , 0
9838.787    0.12       09838.787    0.12       010161.28    0.12       0
#XS Ineff= 2 , 0
       0                               0
Bank Sta=9838.787,10161.28
Exp/Cntr=0.3,0.1

Type RM Length L Ch R = 1 ,2044.117,48.192400,48.192400,48.192400
XS GIS Cut Line= 6
1200802.01240131841258.2823145441200853.63995632841237.483258672
1200887.81460907841217.9658331871200907.37717018 841202.83925848
1200998.18016563 841123.49448803 1201064.3857625841074.803007332
#Sta/Elev= 30
9838.73987.220889842.63786.896319849.71186.720519853.24886.336819863.87884.28168
9872.65782.845189885.08181.245889895.78179.567649911.09478.050479914.672 77.4708
9929.78474.403829937.69173.72173  9942.2 72.93319950.13371.142649958.42768.62366
9962.918 68.07679967.90967.945249977.50868.197449991.71568.8755910017.7169.56706
10028.4769.6032210042.8470.2547310050.1370.3736810054.4670.6981710072.9873.46967
10100.0478.6745710116.6681.1096410129.2583.7941210155.4287.58183 10161.388.67862
#Mann= 3 , 0 , 0
9838.739    0.12       09838.739    0.12       0 10161.3    0.12       0
#XS Ineff= 2 , 0
       0                               0
Bank Sta=9838.739,10161.3
Exp/Cntr=0.3,0.1

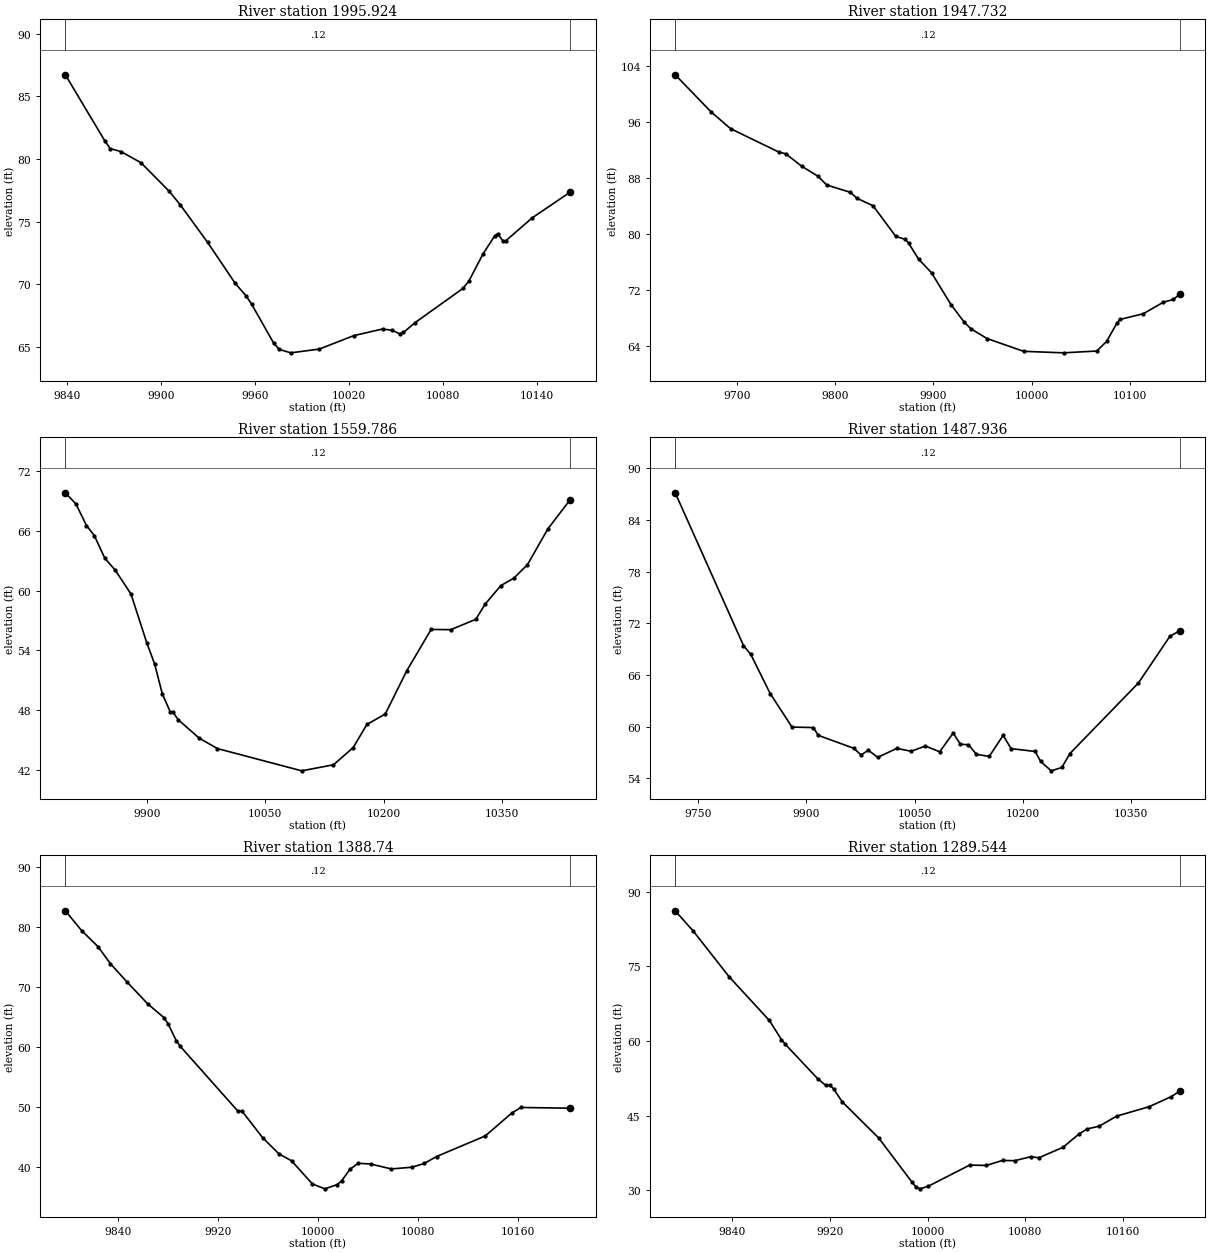
Type RM Length L Ch R = 1 ,1995.924,48.192300,48.192300,48.192300
XS GIS Cut Line= 6
1200814.33450118841269.6198680311200884.56682258841248.063308138
1200949.58888888841223.0395127611200964.86487248841215.223958747
1200966.50761241841214.0831671271201109.53911169841141.719359498
#Sta/Elev= 30
9838.70486.731869863.91581.457059867.34780.842669874.21180.603799886.99579.71533
9905.09877.426589911.96276.377249929.53473.365789947.11170.103799954.14269.08961
9957.65768.433079971.71965.330739975.23464.820599982.71464.5397710000.8664.83728
10022.9365.9115810041.3166.4428310047.4566.3403910052.3466.0561510054.7266.17106
10061.9866.9374210092.7969.6895610096.4670.2615810105.5972.4463310112.8673.85364
10114.8574.0335910118.5373.4321410120.1273.4891910136.9175.30812 10161.377.37488
#Mann= 3 , 0 , 0
9838.704    0.12       09838.704    0.12       0 10161.3    0.12       0
#XS Ineff= 2 , 0
       0                               0
Bank Sta=9838.704,10161.3
Exp/Cntr=0.3,0.1

Type RM Length L Ch R = 1 ,1947.732,387.945700,387.945700,387.945700
XS GIS Cut Line= 4
1200615.00851026841303.9614759831200846.48164064841285.229546353
1200933.45131394841271.8495966351201120.77061018841225.019772559
#Sta/Elev= 30
9637.546102.73299674.08597.417319693.83595.022759743.20891.657589749.79191.44097
9766.24989.639659782.707 88.22219791.55286.969459815.622 85.91539822.20685.07742
9838.66383.995559861.70479.628969871.59479.178089874.91478.628859884.87276.38036
 9898.1574.397089918.06669.819339931.34467.347199937.98366.41034 9954.5864.99854
 9991.7263.17192 10032.362.9556910066.1263.2142810076.27 64.622610086.4167.17606
10089.7967.7346110113.4668.55549 10133.670.18757 10143.970.5927810150.85 71.3961
#Mann= 3 , 0 , 0
9637.546    0.12       09637.546    0.12       010150.85    0.12       0
#XS Ineff= 2 , 0
       0                               0
Bank Sta=9637.546,10150.85
Exp/Cntr=0.3,0.1

Type RM Length L Ch R = 1 ,1559.786,71.850200,71.850200,71.850200
XS GIS Cut Line= 4
1200879.93151501841829.7935005131200916.05737925841594.306385204
1200940.14128879841481.9148074391201102.03868052841245.089697152
#Sta/Elev= 30
9796.52869.828419810.00568.697239823.28266.54012 9833.2465.528249846.51763.25894
9859.79462.046469879.70959.653999899.624 54.77859909.58252.649369919.53949.59662
9929.49747.814259932.81647.801869939.45547.032689966.00845.182859989.24344.12525
10096.1241.8869710136.3842.4954510161.3444.2212410178.7846.5537110202.0447.59613
 10229.351.9487710260.1756.0968710284.9456.0699810316.7457.1097410328.6658.64321
10348.5360.5010110364.8161.2398210382.2562.6001310408.1466.1998410436.5969.15231
#Mann= 3 , 0 , 0
9796.528    0.12       09796.528    0.12       010436.59    0.12       0
#XS Ineff= 2 , 0
       09934.711        10054.35       0
Bank Sta=9796.528,10436.59
Exp/Cntr=0.3,0.1

Type RM Length L Ch R = 1 ,1487.936,99.195700,99.195700,99.195700
XS GIS Cut Line= 5
1200934.78930888841915.4251787961200969.52964306841755.925234631
 1200990.9850978841546.1385661511201081.87322146841371.011043444
1201136.82654986 841255.79365693
#Sta/Elev= 30
9718.50987.148189813.06669.419729823.13968.391539850.00163.853929880.22159.95849
 9909.9359.902079916.52658.999729965.99557.491269975.88956.712089985.78357.28147
9998.97456.4467410025.3657.4891110045.1557.1493710064.9357.7583610084.7257.09059
10103.3359.2687710113.3457.9652910124.4357.9149110135.5156.8007610153.1956.55002
10172.4858.9911910183.5757.4552810216.8357.1291410224.4155.9868510239.0154.88003
 10253.855.2698310264.8956.8819910359.8165.0784210403.43 70.497310417.5971.16408
#Mann= 3 , 0 , 0
9718.509    0.12       09718.509    0.12       010417.59    0.12       0
#XS Ineff= 2 , 0
       0 9936.41        10056.93       0
Bank Sta=9718.509,10417.59
Exp/Cntr=0.3,0.1

Type RM Length L Ch R = 1 , 1388.74,99.195800,99.195800,99.195800
XS GIS Cut Line= 6
1201084.28014808841835.9757049391201090.21265651841714.750178097
 1201071.8348352 841585.696639911201071.26605951841539.274723213
1201083.69984894841496.9185986931201118.63393549841446.979891365
#Sta/Elev= 30
9798.05882.722959811.06279.426589824.24976.73132 9834.1473.889179847.32770.86396
9863.77167.237519876.89564.908129880.17563.895089886.73761.071349890.01860.11185
 9936.0249.327799939.31549.34073 9955.7944.90081 9968.9742.184189978.96541.04066
9995.62337.1859410005.6336.3692710015.6137.0899510018.9437.6873510025.5939.61479
10032.2540.6287210042.2340.5064610058.7639.68853 10075.239.9714610085.0540.59991
 10094.941.7554210133.8545.1864410155.0448.99642 10162.349.9321710201.8949.81189
#Mann= 3 , 0 , 0
9798.058    0.12       09798.058    0.12       010201.89    0.12       0
#XS Ineff= 2 , 0
       0                               0
Bank Sta=9798.058,10201.89
Exp/Cntr=0.3,0.1

Type RM Length L Ch R = 1 ,1289.544,99.195700,99.195700,99.195700
XS GIS Cut Line= 6
1201201.52259242841821.3910311891201195.79159427841699.898422512
1201165.12915873841568.4056342951201158.32744887841522.420772015
1201162.47617265841464.4431101031201181.21338692841416.065739633
#Sta/Elev= 30
9793.15186.168739807.91282.10349 9837.4472.883559870.31464.12883  9880.260.29093
9883.49659.314079909.85952.439079916.46951.088099919.80651.145939923.14350.33477
9929.81647.834739959.84940.528889986.89331.732989990.28730.722659993.681  30.314
10000.5230.8459310034.4135.0910310047.95 35.011710061.2636.0155710071.2135.97125
10084.4836.7666110091.1136.5581910110.8638.6640510123.9841.3424610130.5742.33923
10140.5342.90911 10154.844.9212710181.4346.8215710199.3448.8183810206.7949.98285
#Mann= 3 , 0 , 0
9793.151    0.12       09793.151    0.12       010206.79    0.12       0
#XS Ineff= 2 , 0
       0                               0
Bank Sta=9793.151,10206.79
Exp/Cntr=0.3,0.1

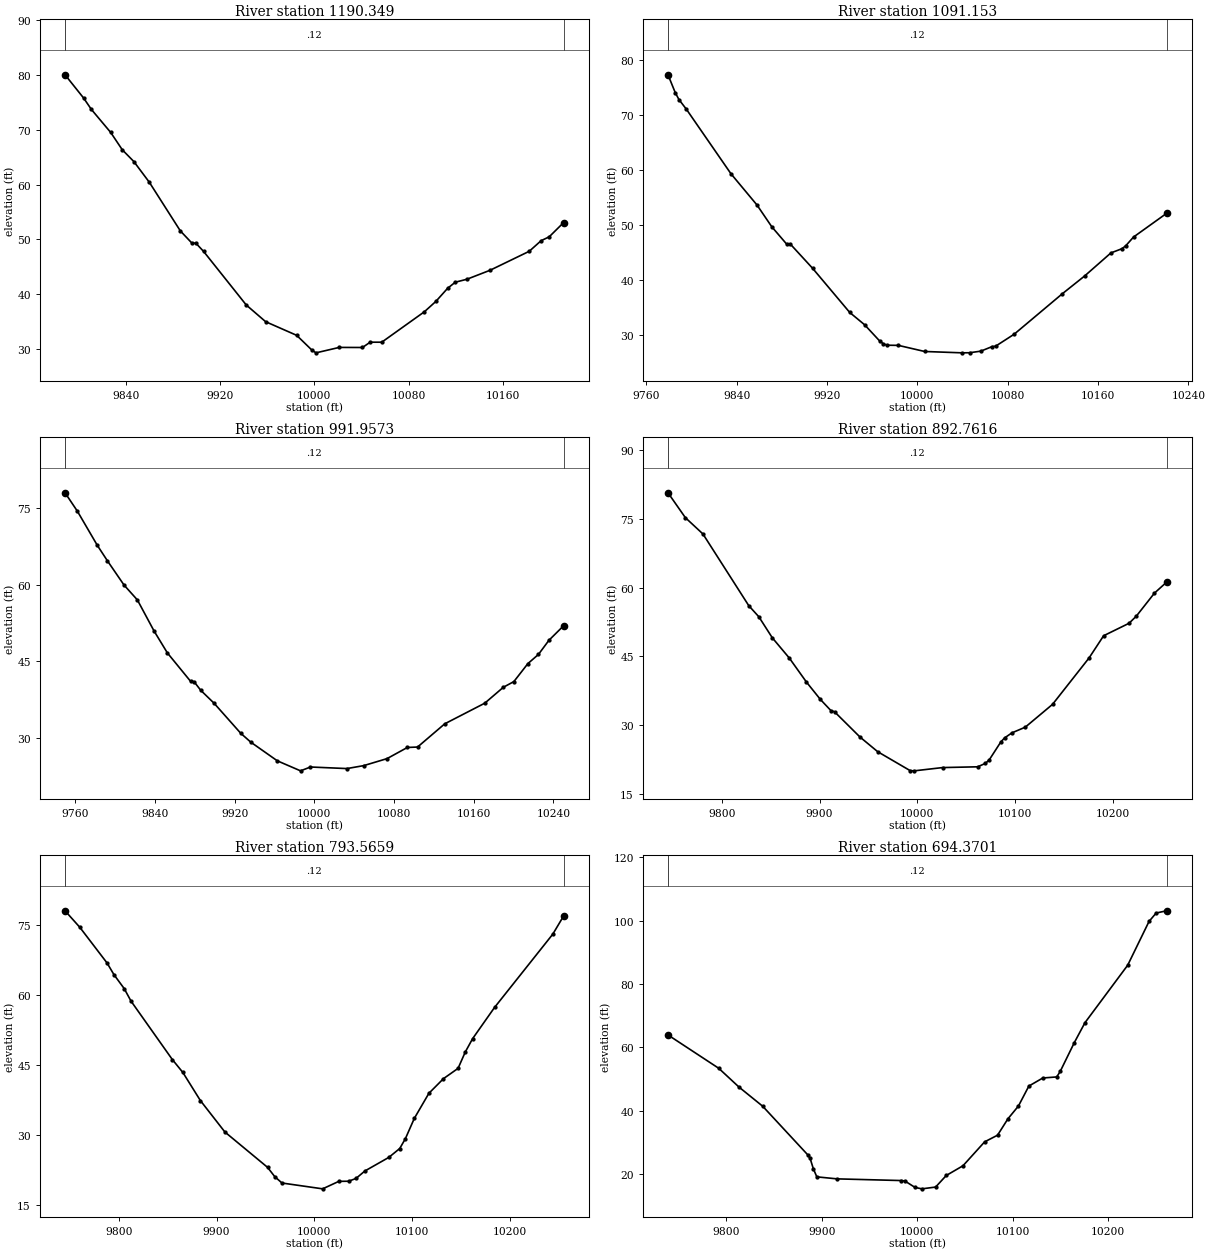
Type RM Length L Ch R = 1 ,1190.349,99.195700,99.195700,99.195700
XS GIS Cut Line= 6
1201285.66179213841806.0430930011201284.89207545841730.319519194
1201274.74371648841618.6208936541201267.89715282841488.824072978
1201270.66815446 841440.151324281201283.03094373841384.695423187
#Sta/Elev= 30
9788.23880.045619804.05675.784369810.61873.718039827.02369.514919836.86666.34718
9846.70964.192589859.83360.418519886.17151.535419896.05449.293529899.349 49.2969
9905.93747.784259942.17537.999219958.64734.94978 9984.9832.462389998.12629.72361
10001.4129.2644210021.1230.2543610040.8430.2410710047.4131.2083310057.2631.20705
 10093.436.7561710103.2538.6644410113.1141.0323710119.6842.1630410129.5442.70035
10149.2644.3469710182.5147.8083610192.6349.7510110199.4550.4477610211.7453.05901
#Mann= 3 , 0 , 0
9788.238    0.12       09788.238    0.12       010211.74    0.12       0
#XS Ineff= 2 , 0
       0                               0
Bank Sta=9788.238,10211.74
Exp/Cntr=0.3,0.1

Type RM Length L Ch R = 1 ,1091.153,99.195800,99.195800,99.195800
XS GIS Cut Line= 6
1201375.68471076841803.1364651571201382.49242839841670.491402206
1201364.62666223841538.3531511631201361.81049243841487.475512311
1201365.59064195841429.2993107161201379.45260114841364.911293236
#Sta/Elev= 30
9779.22777.307739785.60274.085569788.896 72.81559795.48571.058029835.017 59.3218
9858.02753.658189871.15249.696539884.27646.560579887.55746.559289907.24342.16816
9940.16134.140349953.33531.90436 9966.5928.974619969.91628.454889973.24228.19042
9983.22128.16276 10006.527.0527910039.69  26.80710046.3226.8245510056.1827.11216
10066.0427.9242610069.3228.0144310085.7530.1885510128.49 37.552810148.2140.77433
10171.4344.9546810181.4245.7384210184.7546.2969710191.4847.8408910220.7452.14156
#Mann= 3 , 0 , 0
9779.227    0.12       09779.227    0.12       010220.74    0.12       0
#XS Ineff= 2 , 0
       0                               0
Bank Sta=9779.227,10220.74
Exp/Cntr=0.3,0.1

Type RM Length L Ch R = 1 ,991.9573,99.195700,99.195700,99.195700
XS GIS Cut Line= 6
1201421.70472135841822.0427601931201461.38260842841625.728994125
1201474.85457835841545.7493925661201484.56338881841500.223544845
1201508.88363982  841416.06299011201539.86481948841336.881421908
#Sta/Elev= 30
9749.68477.998869762.061 74.39249782.14467.673859792.18664.674429808.92159.90935
 9822.31 56.99339839.04650.906289852.43546.601429875.86541.000659879.212 40.9652
9885.90639.278169899.29536.742559926.07330.849729936.11429.115769962.81725.44709
9986.112 23.48469996.09624.23672 10032.723.9295110049.4724.5042810072.9525.87969
10093.3628.06689 10103.628.1517810130.9232.7079110171.0636.7469310189.7339.87025
 10200.340.9852410214.3944.5167210224.9646.3087410235.5349.0880110250.2551.93375
#Mann= 3 , 0 , 0
9749.684    0.12       09749.684    0.12       010250.25    0.12       0
#XS Ineff= 2 , 0
       0                               0
Bank Sta=9749.684,10250.25
Exp/Cntr=0.3,0.1

Type RM Length L Ch R = 1 ,892.7616,99.195700,99.195700,99.195700
XS GIS Cut Line= 6
1201455.48372899841856.5352169241201487.73951747841747.050294382
1201514.07037882841684.2940004621201535.32903486841648.863299384
1201604.34510302841552.6856875141201684.97461136  841405.2633295
#Sta/Elev= 30
9744.98380.69975 9762.7375.273129780.73271.706129827.59456.060269837.92553.62793
9851.70149.037229869.10444.612229886.64739.366969900.88835.580479911.73533.12802
9915.35132.890379941.44127.364699959.54624.168899992.81320.026329996.91519.99494
10025.8420.7074310061.8120.8754410069.6821.6257210073.6122.3910410085.4226.28618
10089.2627.1744710096.8128.2877810110.4829.5278510138.38  34.51410175.7644.64977
10190.6249.4872610216.6452.2111210224.0753.7649610242.6558.8015510255.0561.18538
#Mann= 3 , 0 , 0
9744.983    0.12       09744.983    0.12       010255.05    0.12       0
#XS Ineff= 2 , 0
       0                               0
Bank Sta=9744.983,10255.05
Exp/Cntr=0.3,0.1

Type RM Length L Ch R = 1 ,793.5659,99.195800,99.195800,99.195800
XS GIS Cut Line= 6
1201533.89188714841912.6037817661201568.73057089841818.694193815
1201604.47292028841737.6117381131201624.03972969841700.011027737
1201657.04167009841643.5577902851201758.58245228841455.701302076
#Sta/Elev= 30
9744.965 78.01859760.01574.49814 9788.0166.828719795.00864.343699805.50661.35877
9812.50558.668839854.72746.173519865.48443.413659883.41137.398689908.50930.65928
9952.09623.104539959.49321.11099 9966.8919.7398210008.5118.4922710025.0920.09703
10035.0620.1202310042.62 20.717210051.7922.3224710076.1925.2202810087.3827.12492
10093.1929.2403410102.2933.5754410117.2138.9462410132.1342.0821610147.0544.28282
10154.5147.8195810161.9650.6511510184.34 57.315210244.0173.0268610255.0676.91531
#Mann= 3 , 0 , 0
9744.965    0.12       09744.965    0.12       010255.06    0.12       0
#XS Ineff= 2 , 0
       0                               0
Bank Sta=9744.965,10255.06
Exp/Cntr=0.3,0.1

Type RM Length L Ch R = 1 ,694.3701,99.195700,99.195700,99.195700
XS GIS Cut Line= 6
1201629.37700956841954.2553189021201720.51211487841730.883165811
1201728.79742602841711.689511157 1201755.2042224841652.002154083
1201793.95506319841572.3012679721201844.33958828841478.754156507
#Sta/Elev= 30
9738.84663.894589791.98453.366039813.24447.417979838.04841.369539885.80125.83471
9887.65624.945849891.19921.531249894.74219.057539916.003 18.42169983.35417.88886
9986.92617.758289997.64415.7168710004.8115.2724210019.1615.8334210030.3319.48938
10047.8622.5671810070.53 30.120310084.0332.2157510094.9837.4220510105.9241.43244
10116.8647.7461710131.4650.2949610146.0550.63025 10149.752.3703410164.4961.48534
10175.67 67.786410220.3985.9292910242.7599.76611 10250.2102.416710261.14103.1266
#Mann= 3 , 0 , 0
9738.846    0.12       09738.846    0.12       010261.14    0.12       0
#XS Ineff= 2 , 0
       0                               0
Bank Sta=9738.846,10261.14
Exp/Cntr=0.3,0.1

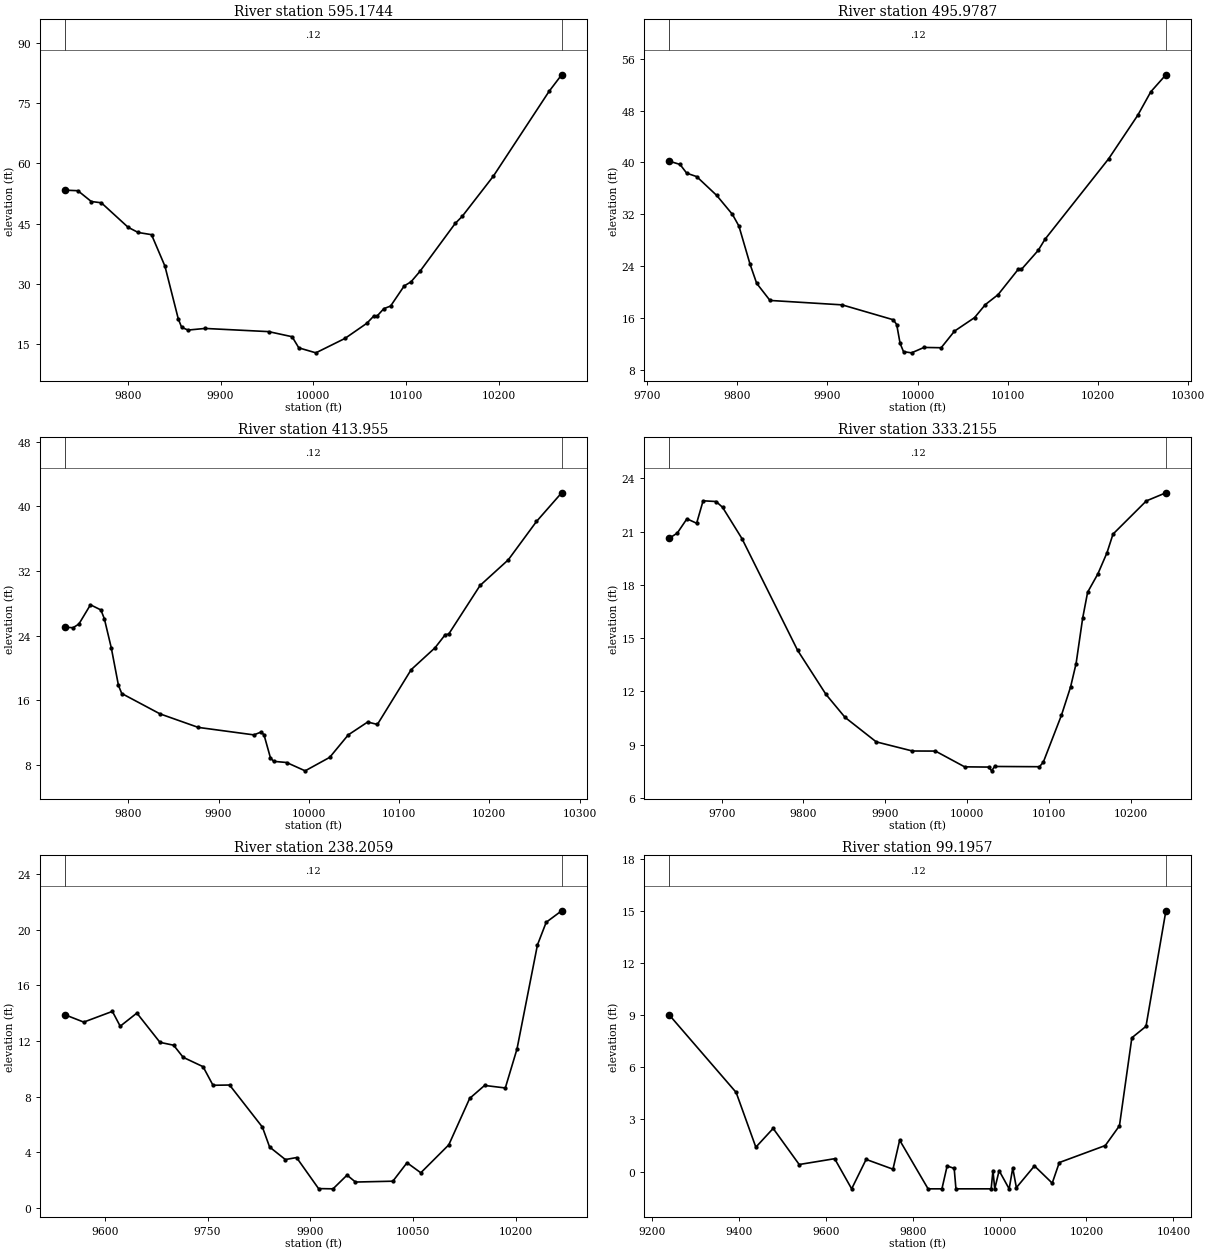
Type RM Length L Ch R = 1 ,595.1744,99.195700,99.195700,99.195700
XS GIS Cut Line= 6
1201704.94351603841999.7663346581201810.39659177 841770.13380619
1201816.82522264841757.4681544891201817.75873983841755.699384957
1201885.73866094841619.2306900091201940.81980962 841518.94318822
#Sta/Elev= 30
9732.10853.333329746.07353.192679760.51350.498919771.34450.180729800.22644.06555
9811.05742.768349825.49842.219479839.93934.37671 9854.3821.17072 9857.9919.08747
9864.875 18.40099883.26218.806359951.85618.011039977.12816.738369984.34813.95962
10002.75 12.714610034.13 16.311110057.7320.0936210065.0621.8617210068.7221.88528
10076.0523.7399810083.3824.4033210098.0529.4247310105.3830.4420710115.0733.07076
10153.0345.01816 10160.546.7618710194.1956.82529 10254.277.9687810267.8882.13888
#Mann= 3 , 0 , 0
9732.108    0.12       09732.108    0.12       010267.88    0.12       0
#XS Ineff= 2 , 0
       0                               0
Bank Sta=9732.108,10267.88
Exp/Cntr=0.3,0.1

Type RM Length L Ch R = 1 ,495.9787,82.023700,82.023700,82.023700
XS GIS Cut Line= 6
1201780.64821282842040.4158728311201893.82034654841821.321288066
1201907.50572257841797.2672267451201921.09316476 841773.75410418
1201988.40965555841646.8274690061202041.92697133 841555.99229646
#Sta/Elev= 30
9724.72840.196329736.75939.688669744.14438.341339755.22237.811839777.37834.91123
9794.88131.97136 9802.0330.178249814.30524.31679 9821.6921.344769836.46118.69992
 9916.4118.016929973.12915.716589976.90414.973819980.67912.065229984.45310.79357
9993.34110.6132510007.1711.44707 10026.211.4003910040.9413.9624910063.2216.05231
10075.2118.0667710089.2219.58624 10111.523.4865710115.2123.5023410133.7826.43311
10141.2128.1288310211.7640.5525810244.0847.2791810258.5350.9018610275.2653.52503
#Mann= 3 , 0 , 0
9724.728    0.12       09724.728    0.12       010275.26    0.12       0
#XS Ineff= 2 , 0
       0                               0
Bank Sta=9724.728,10275.26
Exp/Cntr=0.3,0.1

Type RM Length L Ch R = 1 , 413.955,80.739500,80.739500,80.739500
XS GIS Cut Line= 6
1201847.38314829 842070.220090021201959.99646508841887.167791284
 1201973.8600473 841855.981648651201990.74316432841794.344376585
1202007.31547831 841757.277857071202110.33087428841589.646226563
#Sta/Elev= 30
9729.83925.051329738.86224.987199745.31925.449469758.121 27.82829769.67727.18872
9773.52926.091419781.23322.477289789.14917.839019792.78916.842579835.161  14.322
9877.53212.646539939.16411.719999946.724 12.04939950.31511.765159957.4968.894118
9961.0868.4435539975.4488.2991739995.9957.26690710023.218.93647210043.72 11.7141
10065.2813.3108510076.0613.0114410113.4819.7955510139.9422.5075710151.2824.13554
10155.0624.2018710189.7930.2172110221.0633.3936210252.3338.1442910280.2341.69772
#Mann= 3 , 0 , 0
9729.839    0.12       09729.839    0.12       010280.23    0.12       0
#XS Ineff= 2 , 0
       09925.412                       0
Bank Sta=9729.839,10280.23
Exp/Cntr=0.3,0.1

Type RM Length L Ch R = 1 ,333.2155,95.009600,95.009600,95.009600
XS GIS Cut Line= 6
1201830.09824237842149.4439068291201942.79673153841982.138933197
1201975.32825422841927.5324487541202024.12553817841879.897004887
1202131.01482689841821.8050001411202201.88707268841687.031549186
#Sta/Elev= 30
9635.77720.625419645.62620.914579657.49321.723289669.36121.471879677.27222.73781
9693.09522.697959701.00722.375289724.74120.612219792.81114.314189827.59111.82433
9850.847 10.53319889.0369.1513429933.2398.637215 9961.428.6323759997.1367.744424
10026.487.73110810030.157.51886610033.827.76481610088.637.75110710093.32 8.00596
10115.5710.6572610126.6912.2442610133.4513.5682610141.5116.1300110147.5517.58617
10160.0518.6158510171.1719.8025310178.5820.8598810219.3622.7317710243.2823.18998
#Mann= 3 , 0 , 0
9635.777    0.12       09635.777    0.12       010243.28    0.12       0
#XS Ineff= 2 , 0
       0  9905.8        10088.83       0
Bank Sta=9635.777,10243.28
Exp/Cntr=0.3,0.1

Type RM Length L Ch R = 1 ,238.2059,139.010200,139.010200,139.010200
XS GIS Cut Line= 6
  1201788.271999842271.4371167571202001.53837213842074.388514057
1202101.82628062841940.0629919321202128.50799298841907.371526495
1202213.65233189 841809.818037511202274.14369181841736.742470369
#Sta/Elev= 30
9541.91513.882159569.34313.353519611.10514.122989622.52313.05794 9646.8414.00102
9680.537 11.90029700.44211.693879714.37910.825059743.38610.153329757.8898.817898
9782.0628.8364669829.9815.8117579840.4394.386347 9863.423.4850049879.7833.627643
9911.8481.4004039932.9611.3821529953.414 2.367719965.6861.87018510020.24 1.93099
10040.873.255794   100612.535484 10101.84.54093910132.287.87682310154.05  8.8063
10184.258.62483910201.2911.42083 10231.118.8889310243.8820.5199710266.4621.34664
#Mann= 3 , 0 , 0
9541.915    0.12       09541.915    0.12       010266.46    0.12       0
#XS Ineff= 2 , 0
       09926.924        10100.42       0
Bank Sta=9541.915,10266.46
Exp/Cntr=0.3,0.1

Type RM Length L Ch R = 1 , 99.1957,0.000000,0.000000,0.000000
XS GIS Cut Line= 6
1201703.45767203842587.4576224831202121.32307923842149.315709516
1202199.36235324842041.5616461491202213.11154291842023.378177986
 1202266.5164915841954.8625584241202441.22613212841717.239391655
#Sta/Elev= 30
  9239.79.0265669393.8314.5565519439.1681.4004889479.0062.482686 9538.910.402729
9620.5170.7378029659.647  -0.9999692.922 0.697099754.7210.1328319770.1291.803263
9835.534  -0.9999867.394  -0.9999879.3910.3207389895.5950.1774589899.646  -0.999
9980.701  -0.9999984.8130.0527419988.925  -0.999    99990.04887210022.07  -0.999
10030.390.20010710038.71-0.9299410080.310.32139110121.19-0.6700410137.480.516059
10243.351.49618210275.932.63687610304.437.70413510337.018.36507910382.8115.02291
#Mann= 3 , 0 , 0
  9239.7    0.12       0  9239.7    0.12       010382.81    0.12       0
#XS Ineff= 2 , 0
       09868.566        10110.72       0
Bank Sta=9239.7,10382.81
Exp/Cntr=0.3,0.1